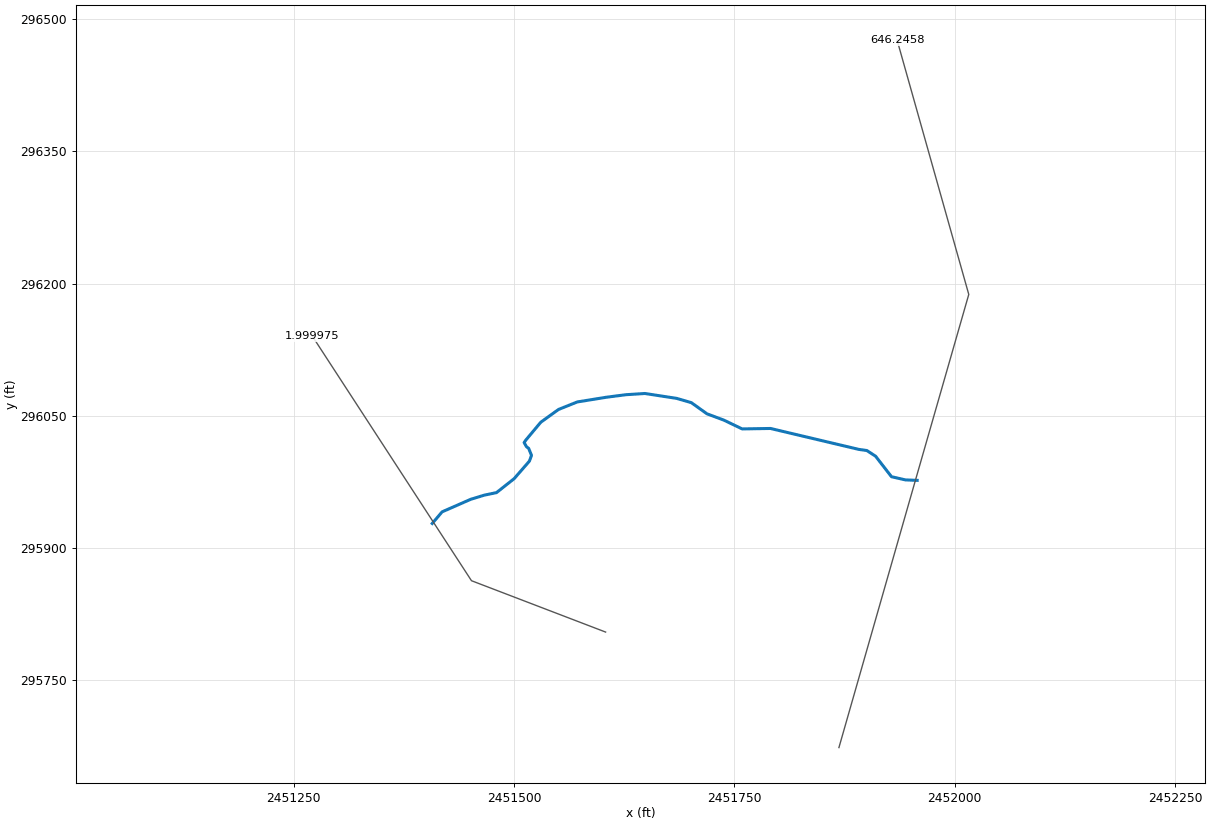
--- FlowingSpringsRun.prj (project) ---

Proj Title=FlowingSpringsRun
Current Plan=p01
Default Exp/Contr=0.3,0.1
English Units
Geom File=g01
Flow File=f01
Plan File=p01
Y Axis Title=Elevation
X Axis Title(PF)=Main Channel Distance
X Axis Title(XS)=Station
BEGIN DESCRIPTION:
END DESCRIPTION:
DSS Export Rating Curves= 0
DSS Export Rating Curve Sorted= 0
DSS Export Volume Flow Curves= 0
DXF OffsetX= 0
DXF OffsetY= 0
DXF ScaleX= 1
DXF ScaleY= 10

--- FlowingSpringsRun.p01 (plan) ---

Plan Title=Plan 01
Program Version=4.10
Short Identifier=Plan 01
Geom File=g01
Flow File=f01
Subcritical Flow
K Sum by GR= 0
Std Step Tol= 0.01
Critical Tol= 0.01
Num of Std Step Trials= 20
Max Error Tol= 0.3
Flow Tol Ratio= 0.001
Split Flow NTrial= 30
Split Flow Tol= 0.02
Split Flow Ratio= 0.02
Log Output Level= 0
Friction Slope Method= 1
Unsteady Friction Slope Method= 2
Unsteady Bridges Friction Slope Method= 1
Parabolic Critical Depth
Global Vel Dist= 0 , 0 , 0
Global Log Level= 0
CheckData=True
Encroach Param=-1 ,0,0, 0
Computation Interval=1HOUR
Output Interval=1HOUR
Run HTab= 0
Run UNet= 0
Run PostProcess= 0
Run WQNet= 0
UNET Theta= 1
UNET Theta Warmup= 1
UNET ZTol= 0.02
UNET ZSATol= 0.05
UNET MxIter= 20
UNET MaxInSteps= 0
UNET DtIC= 0
UNET DtMin= 0
UNET MaxCRTS= 20
UNET WFStab= 2
UNET SFStab= 1
UNET WFX= 1
UNET SFX= 1
UNET DSS MLevel= 4
UNET DZMax Abort= 100
UNET Convert EG Bridges= 0
UNET Use Existing IB Tables=-1
UNET Froude Reduction=False
UNET Froude Limit= 1
UNET Froude Power= 10
UNET Time Slicing=0,0, 5
UNET Junction Losses=0
Instantaneous Interval=1HOUR
Write IC File= 0
Write IC File at Sim End=0
Echo Input=False
Echo Parameters=False
Echo Output=False
Write Detailed= 0
WQ AD Non Conservative
WQ ULTIMATE=-1
WQ Max Comp Step=1HOUR
WQ Output Interval=15MIN
WQ Output Selected Increments= 0
WQ Output face flow=0
WQ Output face velocity=0
WQ Output face area=0
WQ Output face dispersion=0
WQ Output cell volume=0
WQ Output cell surface area=0
WQ Output cell continuity=0
WQ Output cumulative cell continuity=0
WQ Output face conc=0
WQ Output face dconc_dx=0
WQ Output face courant=0
WQ Output face peclet=0
WQ Output face adv mass=0
WQ Output face disp mass=0
WQ Output cell mass=0
WQ Output cell source sink temp=0
WQ Output cell source sink nsm=0
WQ Output MaxMinRange=-1
WQ Daily Max Min Mean=-1
WQ Daily Range=0
WQ Daily Time=0
WQ Create Restart=0
WQ Fixed Restart=0
WQ System Summary=0
WQ Use Fixed Temperature=0
Sorting and Armoring Iterations= 10
XS Update Threshold= 0.02
Hydraulics Update Threshold= 0.02
Energy Slope Method= 1
Volume Change Method= 0
XS Weighting Method= 0
Number of US Weighted Cross Sections= 1
Number of DS Weighted Cross Sections= 1
Upstream XS Weight=0.25
Main XS Weight=0.5
Downstream XS Weight=0.25
Number of DS XS's Weighted with US Boundary= 1
Upstream Boundary Weight= 1
Weight of XSs Associated with US Boundary= 0
Number of US XS's Weighted with DS Boundary= 1
Downstream Boundary Weight= 0.5
Weight of XSs Associated with DS Boundary= 0.5
Sediment Output Level= 4
Mass or Volume Output= 0
Output Increment Type= 1
Profile and TS Output Increment= 10
XS Output Flag= 0
XS Output Increment= 10
Disregard all LS=0
Disregard all Conn=0
Disregard all Breaches=0
Disregard all Pumps=0

--- FlowingSpringsRun.f01 (steady flow) ---

Flow Title=FlowingSpringsRun
Program Version=4.10
Number of Profiles= 1
Profile Names=PF 1
River Rch & RM=FlowingSprngsRun,Reach1          ,646.2458
    1730
Boundary for River Rch & Prof#=FlowingSprngsRun,Reach1          , 1
Up Type= 0
Dn Type= 1
Dn Known WS=352.79
DSS Import GetInterval= 0
DSS Import GetPeak= 0
DSS Import FillOption= 0

--- FlowingSpringsRun.g01 (geometry) ---

Geom Title=FlowingSpringsRun
Program Version=4.10

River Reach=FlowingSprngsRun,Reach1
Reach XY= 30
2451957.31680502295976.6458313472451943.94872153  295977.1664996
2451928.17316252295980.7777128522451910.11775245296004.041445851
2451900.19880903296010.4997662752451891.12303978296011.787493348
 2451790.8414162296035.5344931042451758.69384269296035.025963932
 2451737.8966402296045.0269281862451718.77495928296052.166677684
2451701.08995527296064.8054319322451684.42332195296069.666642681
2451648.31217369296075.2220777722451626.78432961296073.833301023
2451604.59572569296070.9514170142451571.62564728 296065.62235944
2451550.28546686296057.0711954392451530.21332853296042.606329352
2451513.26290311296022.3750706022451511.31835319296019.527635351
2451513.95745553296014.8750856072451516.45056078296012.993199602
 2451519.6864467 296004.987638192451517.29931235295998.477480605
2451499.98733911295978.5713524372451480.02215594 295962.77282761
2451465.95984811295959.8213899432451450.68199153295955.133735269
2451418.21650527 295940.897871362451407.02820744295927.703343943

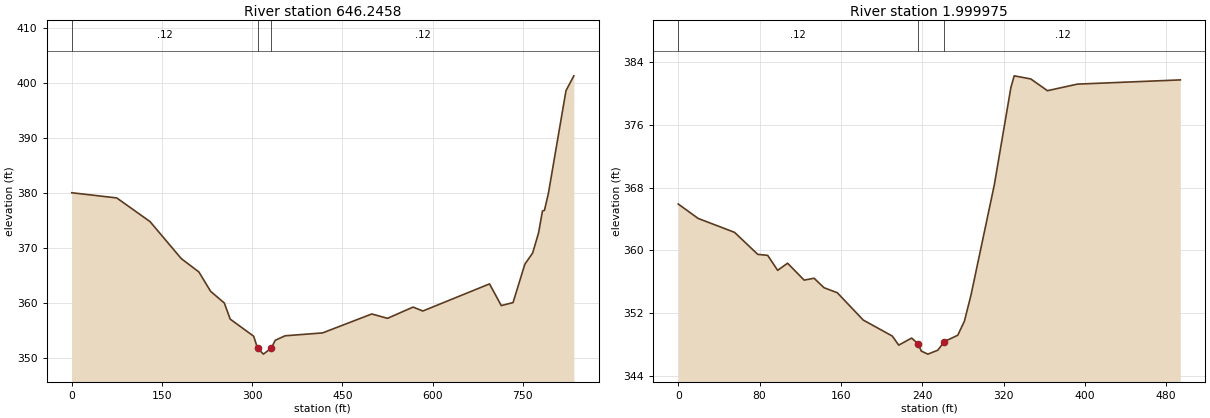
Type RM Length L Ch R = 1 ,646.2458,611.09,644.25,662.82
Node Name=981
XS GIS Cut Line= 4
 2451868.5203947295673.4282619362451955.31844944295976.723587111
2452015.85999502296187.6322860272451934.49270369296476.379411936
#Sta/Elev= 30
       0     380    74.8  379.06  130.09  374.77  182.13  368.04   211.4  365.62
  230.91   362.1  253.68  359.98  263.43  357.06  302.46  353.95  308.97  351.77
  318.75   350.7  331.85  351.82   338.4  353.22  354.77  354.03     417  354.55
  498.87  357.99  525.07   357.2   567.5  359.24  583.81  358.53  694.68  363.45
  714.24  359.51   733.8  360.06  753.37  367.02  766.41  369.07   776.2  372.71
  782.72  376.69  785.98   376.8   792.5  379.84  821.85  398.54  834.89  401.23
#Mann= 3 , 0 , 0
       0     .12       0  308.97    .045       0  331.85     .12       0
Bank Sta=308.97,331.85
XS Rating Curve= 0 ,0
Exp/Cntr=0.3,0.1

Type RM Length L Ch R = 1 ,1.999975,5.56,2,14.2
Node Name=982
XS GIS Cut Line= 4
2451603.76337828295804.5044433472451451.56223911295862.777620763
2451408.32184002295929.2286033482451271.09311186296140.118273437
#Sta/Elev= 30
       0  365.92   19.56  364.08   55.41   362.3   78.23  359.49   88.01  359.36
   97.79  357.45  107.56  358.36  123.86   356.2  133.64  356.44  143.42  355.23
  156.46  354.59     182   351.1  210.54  349.06  216.89   347.9  229.57   348.8
  235.91  348.07  239.08  347.14  245.52  346.75  255.33  347.25  261.86  348.36
  274.93  349.16  281.47  350.95     288  354.31  310.88  368.35  327.21  380.79
  330.48  382.29  346.82  381.89  363.16  380.39  392.57  381.23  493.86  381.77
#Mann= 3 , 0 , 0
       0     .12       0  235.91    .045       0  261.86     .12       0
Bank Sta=235.91,261.86
XS Rating Curve= 0 ,0
Exp/Cntr=0.3,0.1

Chan Stop Cuts=-1
Use User Specified Reach Order=0
Composite Channel Slope=5